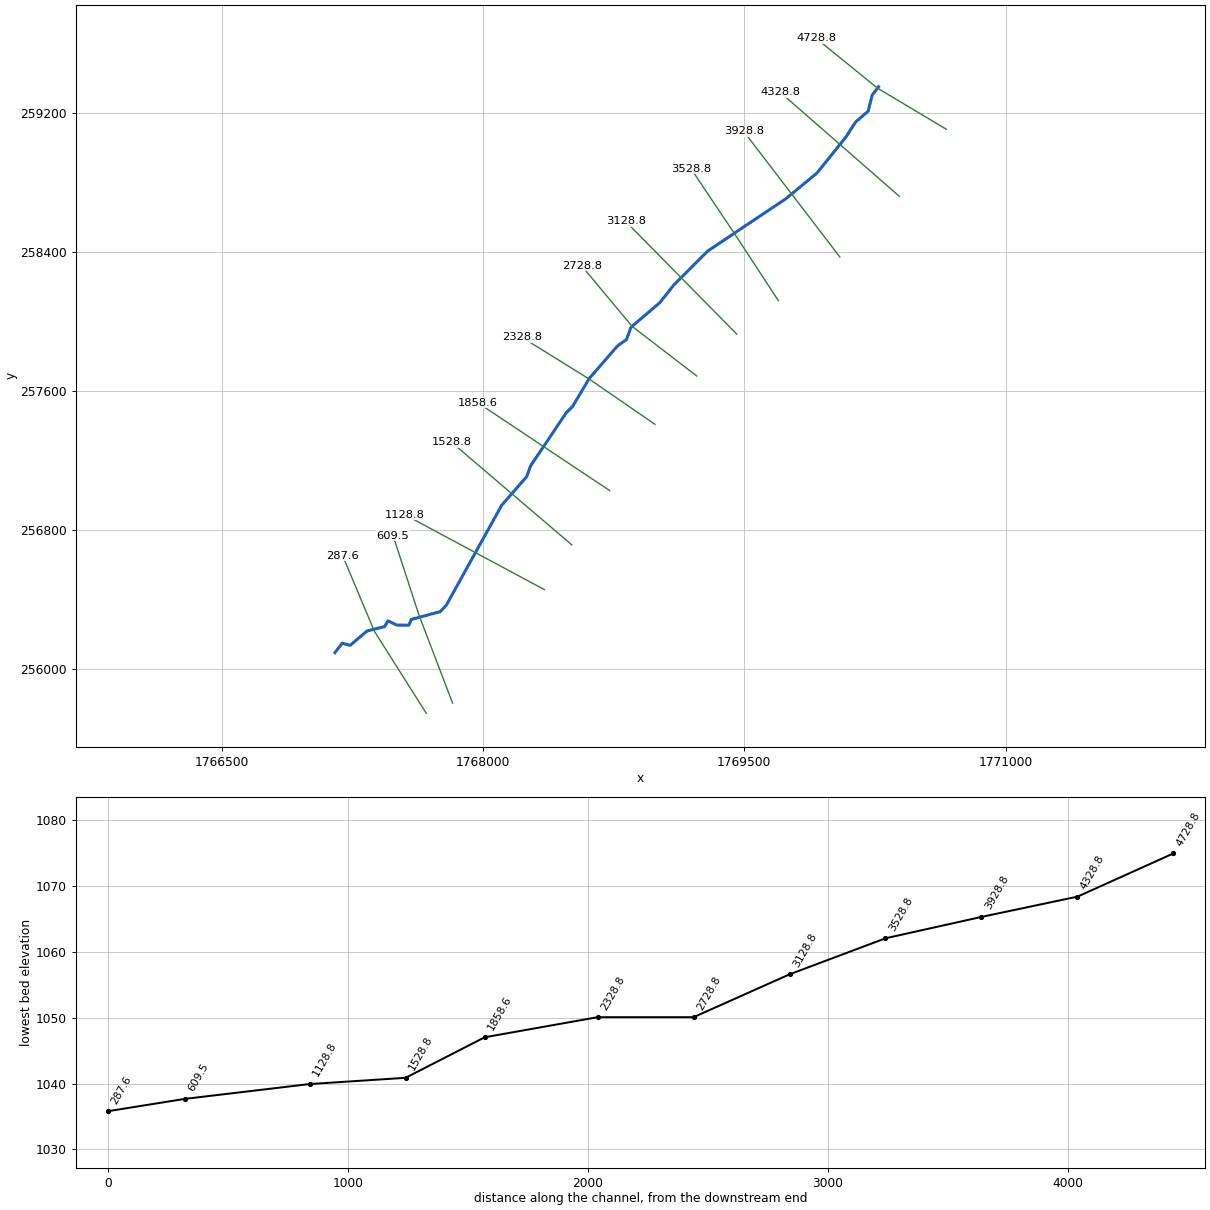
--- StncoalRn.prj (project) ---

Proj Title=StncoalRn
Current Plan=p01
Geom File=g01
Flow File=f01
Plan File=p01
DSS Export Rating Curves=0
DSS Export Rating Curve Sorted=0
DSS Export Volume Flow Curves=0
DXF OffsetX=0
DXF OffsetY=0
DXF ScaleX=0
DXF ScaleY=0

--- StncoalRn.p01 (plan) ---

Plan Title=Floodplain
Program Version=4.00
Geom File=g01
Flow File=f01
K Sum by GR=0
Std Step Tol=0.01
Critical Tol=0.01
Num of Std Step Trials=20
Max Error Tol=0.3
Flow Tol Ratio=0.001
Split Flow NTrial=30
Split Flow Tol=0.02
Split Flow Ratio=0.02
Log Output Level=0
Friction Slope Method=1
Unsteady Friction Slope Method=2
Unsteady Bridges Friction Slope Method=1
Global Log Level=0
CheckData=False
Run HTab=0
Run UNet=0
Run PostProcess=0
UNET Theta=0
UNET Theta Warmup=0
UNET ZTol=0
UNET ZSATol=0
UNET MxIter=0
UNET MaxInSteps=0
UNET DtIC=0
UNET DtMin=0
UNET MaxCRTS=0
UNET WFStab=0
UNET SFStab=0
UNET WFX=0
UNET SFX=0
UNET DSS MLevel=0
UNET DZMax Abort=0
UNET Convert EG Bridges=0
UNET Use Existing IB Tables=0
UNET Froude Limit=0
UNET Froude Power=0
Write IC File=0
Echo Input=False
Echo Output=False
Write Detailed=0

--- StncoalRn.f01 (steady flow) ---

Flow Title=NFF Regression Equation
Program Version=4.00
Number of Profiles=1
Profile Names=P100yr
River Rch & RM=StncoalRn,Main      ,4728.8
907.6610
River Rch & RM=StncoalRn,Main      ,3528.8
940.2714
River Rch & RM=StncoalRn,Main      ,287.6
1043.825
Boundary for River Rch & Prof#=StncoalRn,Main      ,1
Up Type=0
Dn Type=3
Dn Slope=0.007044

--- StncoalRn.g01 (geometry) ---

Geom Title=USGS 3m DEM
Program Version=4.00

River Reach=StncoalRn     ,Main
Reach XY= 30
     1770271.104      259351.690     1770234.423      259303.896
     1770211.345      259211.229     1770139.510      259149.429
     1770083.837      259062.651     1769917.345      258855.263
     1769737.573      258706.378     1769290.201      258406.466
     1769096.242      258212.055     1769015.486      258109.991
     1768849.370      257967.691     1768823.952      257897.235
     1768772.603      257860.925     1768608.870      257671.991
     1768515.216      257513.338     1768478.193      257476.276
     1768274.081      257171.931     1768250.665      257108.487
     1768107.028      256943.361     1767788.585      256367.731
     1767753.925      256331.735     1767587.730      256286.632
     1767575.055      256253.891     1767505.573      256254.394
     1767454.647      256278.502     1767434.351      256245.625
     1767334.369      256220.569     1767237.015      256138.016
     1767191.644      256150.154     1767149.650      256095.558

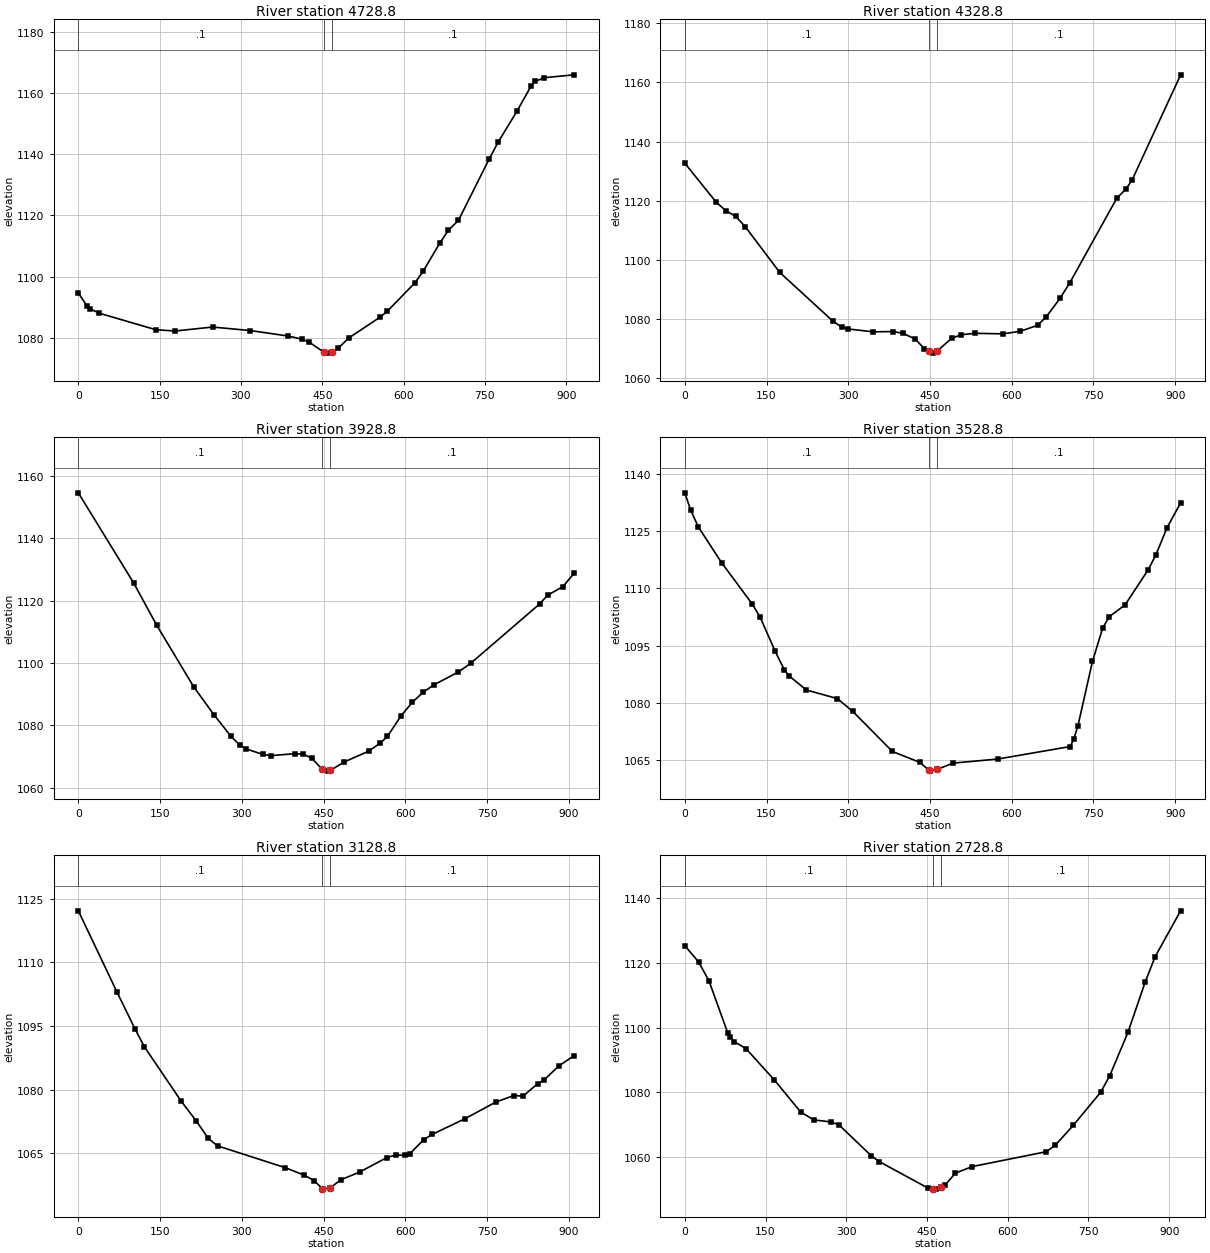
Type RM Length L Ch R = 1 ,4728.8,403.907,400,399.342
XS GIS Cut Line= 3
     1770660.124      259107.313     1770264.794      259343.931
     1769912.575      259630.370
#Sta/Elev= 30
       0 1094.66    16.5 1090.24    21.7 1089.47    38.6 1088.03   142.8 1082.63
   178.3 1082.20   247.7 1083.50   317.0 1082.36   386.4 1080.58   412.2 1079.56
   426.0 1078.55   453.2 1075.25   463.0 1074.97   468.2 1075.19   479.9 1076.66
   498.9 1079.92   555.9 1086.65   569.6 1088.60   621.3 1098.04   636.6 1101.88
   667.2 1111.08   682.5 1115.09   701.3 1118.42   757.7 1138.38   774.3 1143.92
   809.1 1154.06   835.5 1162.40   842.8 1163.84   859.7 1165.06   914.7 1165.99
#Mann= 3 , 0 , 0
       0     0.1       0   453.2   0.045       0   468.2     0.1       0
Bank Sta=   453.2,   468.2
Exp/Cntr=0.3,0.1

Type RM Length L Ch R = 1 ,4328.8,404.509,400,395.491
XS GIS Cut Line= 3
     1770390.082      258721.684     1770047.653      259021.296
     1769705.224      259320.907
#Sta/Elev= 30
       0 1132.67    57.6 1119.47    75.6 1116.58    93.6 1114.64   111.1 1111.15
   174.2 1095.72   271.2 1079.32   288.1 1077.16   300.4 1076.56   346.1 1075.60
   382.1 1075.71   400.1 1075.11   422.7 1073.20   439.5 1069.94   447.5 1069.05
   456.3 1068.40   462.5 1068.99   489.7 1073.41   506.8 1074.60   532.1 1075.11
   584.4 1074.92   615.9 1075.81   647.5 1077.81   663.3 1080.68   688.6 1086.91
   706.7 1092.23   792.9 1120.83   809.7 1123.94   821.0 1127.00   910.0 1162.57
#Mann= 3 , 0 , 0
       0     0.1       0   447.5   0.045       0   462.5     0.1       0
Bank Sta=   447.5,   462.5
Exp/Cntr=0.3,0.1

Type RM Length L Ch R = 1 ,3928.8,401.66,400,398.582
XS GIS Cut Line= 3
     1770049.235      258371.885     1769773.059      258733.481
     1769496.882      259095.076
#Sta/Elev= 30
       0 1154.55   101.6 1125.64   143.9 1112.08   211.7 1092.37   248.8 1083.42
   280.4 1076.43   296.4 1073.67   308.6 1072.42   338.5 1070.68   353.4 1070.29
   398.2 1070.92   413.2 1070.74   428.1 1069.50   447.5 1065.94   458.0 1065.32
   462.5 1065.56   487.9 1068.24   532.7 1071.71   554.2 1074.31   567.4 1076.48
   592.4 1083.08   612.9 1087.36   632.5 1090.57   652.1 1092.93   697.0 1097.05
   719.9 1099.86   846.4 1118.89   861.3 1121.73   889.3 1124.47   910.0 1128.79
#Mann= 3 , 0 , 0
       0     0.1       0   447.5   0.045       0   462.5     0.1       0
Bank Sta=   447.5,   462.5
Exp/Cntr=0.3,0.1

Type RM Length L Ch R = 1 ,3528.8,395.476,400,404.282
XS GIS Cut Line= 3
     1769695.565      258121.445     1769446.774      258502.395
     1769193.881      258880.680
#Sta/Elev= 30
       0 1135.06    10.6 1130.59    24.8 1126.12    67.4 1116.77   124.1 1105.83
   138.3 1102.44   165.5 1093.60   182.7 1088.64   191.3 1087.05   223.3 1083.34
   280.1 1081.09   308.4 1077.72   381.0 1067.22   431.5 1064.37   447.5 1062.36
   450.2 1062.07   462.5 1062.50   493.0 1064.18   574.5 1065.24   707.3 1068.52
   714.0 1070.50   721.5 1073.93   748.2 1090.84   766.7 1099.48   778.7 1102.54
   808.1 1105.68   850.1 1114.79   864.3 1118.68   885.1 1125.93   910.0 1132.43
#Mann= 3 , 0 , 0
       0     0.1       0   447.5   0.045       0   462.5     0.1       0
Bank Sta=   447.5,   462.5
Exp/Cntr=0.3,0.1

Type RM Length L Ch R = 1 ,3128.8,396.798,400,398.164
XS GIS Cut Line= 3
     1769456.948      257928.643     1769137.847      258252.988
     1768818.747      258577.333
#Sta/Elev= 30
       0 1122.11    70.8 1103.02   104.4 1094.21   121.2 1090.11   188.4 1077.37
   216.3 1072.66   238.7 1068.51   255.5 1066.78   380.0 1061.63   413.9 1059.91
   432.9 1058.59   447.5 1056.73   448.6 1056.59   462.5 1056.91   481.6 1058.77
   516.1 1060.60   566.1 1064.01   582.7 1064.63   599.4 1064.53   608.2 1064.89
   634.0 1068.25   649.4 1069.47   708.9 1073.12   766.0 1077.07   799.3 1078.63
   815.9 1078.47   843.2 1081.42   854.1 1082.22   882.5 1085.66   910.0 1088.00
#Mann= 3 , 0 , 0
       0     0.1       0   447.5   0.045       0   462.5     0.1       0
Bank Sta=   447.5,   462.5
Exp/Cntr=0.3,0.1

Type RM Length L Ch R = 1 ,2728.8,398.903,400,407.216
XS GIS Cut Line= 3
     1769227.393      257687.378     1768856.244      257973.302
     1768566.510      258321.065
#Sta/Elev= 30
       0 1125.29    25.5 1120.32    44.9 1114.43    79.8 1098.33    83.8 1097.11
    91.6 1095.67   113.6 1093.51   166.6 1083.77   215.2 1073.92   239.5 1071.48
   271.5 1070.84   286.5 1069.92   346.4 1060.39   361.4 1058.58   451.3 1050.45
     461 1050.20   466.3 1050.08     476 1050.61   484.3 1051.48   502.9 1055.03
   533.8 1057.04   671.5 1061.64   688.4 1063.64   722.1 1069.86   772.7 1080.02
   789.5 1085.12   823.3 1098.50   855.3 1114.04   873.8 1121.88   921.2 1136.07
#Mann= 3 , 0 , 0
       0     0.1       0     461   0.045       0     476     0.1       0
Bank Sta=     461,     476
Exp/Cntr=0.3,0.1

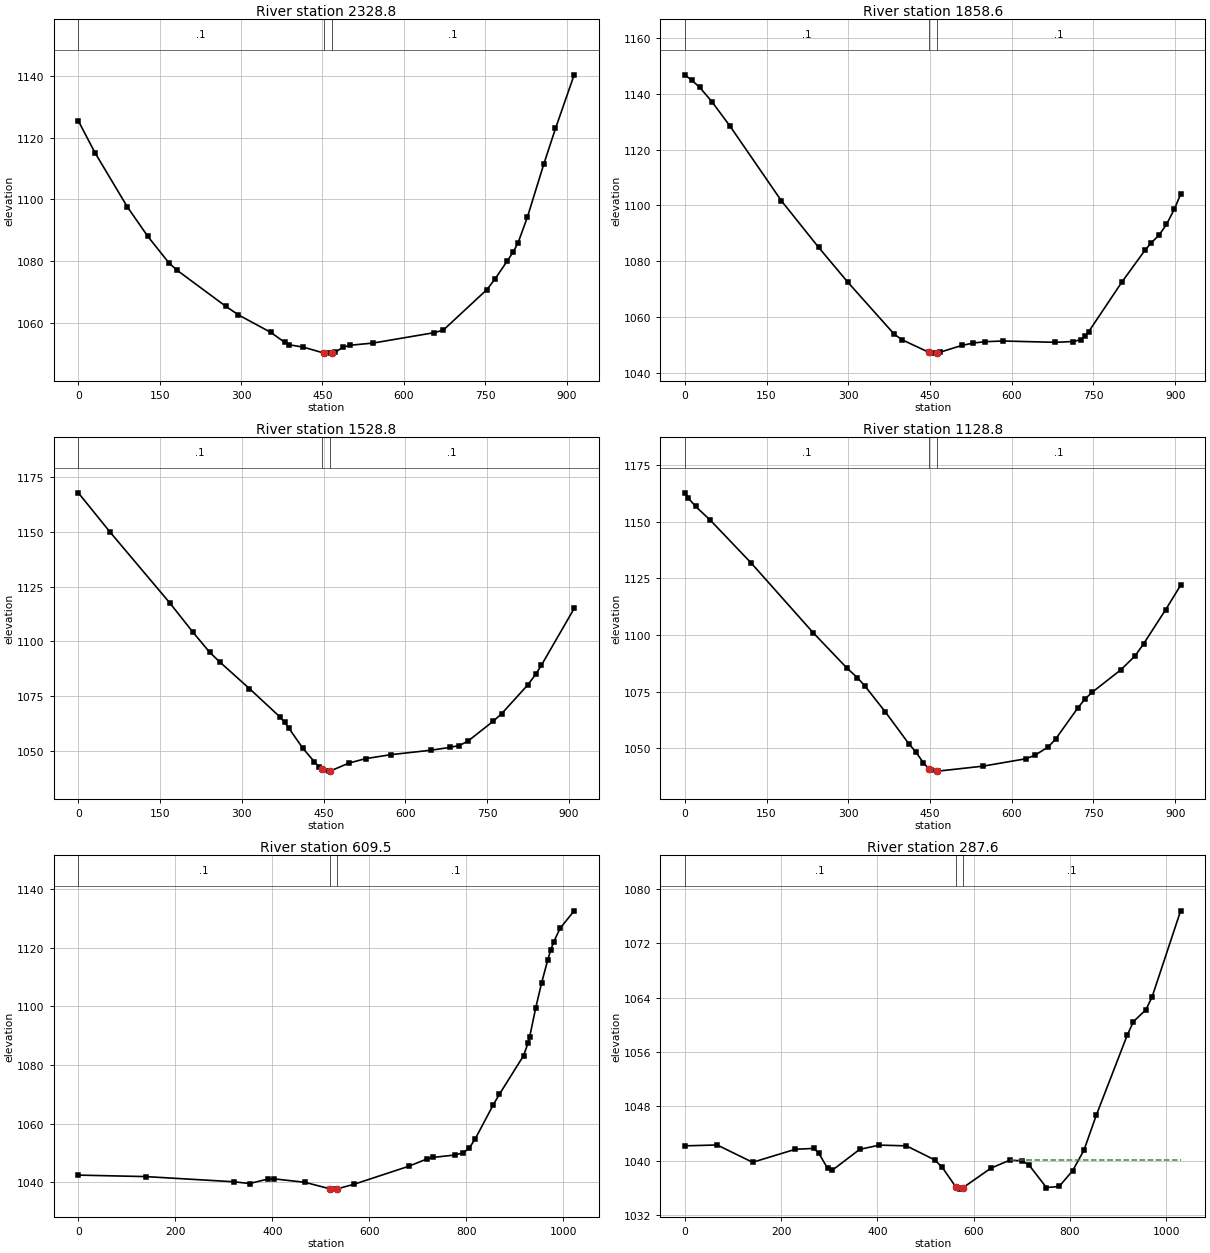
Type RM Length L Ch R = 1 ,2328.8,469.926,470.258,469.508
XS GIS Cut Line= 3
     1768987.097      257409.731     1768608.345      257670.953
     1768222.894      257910.642
#Sta/Elev= 30
       0 1125.40    30.5 1115.13    90.2 1097.54   128.0 1087.96   167.0 1079.34
   181.8 1076.98   272.2 1065.22   295.1 1062.49   354.8 1056.80   380.4 1053.58
   389.0 1052.78   414.6 1052.03   452.6 1050.11   459.7 1050.08   467.6 1050.17
   473.7 1050.37   487.7 1052.00   501.7 1052.65   543.1 1053.34   655.5 1056.70
   672.7 1057.53   753.3 1070.71   768.0 1074.09   790.5 1079.93   802.0 1082.98
   810.7 1085.89   827.9 1094.25   857.9 1111.31   879.6 1122.93   914.0 1140.33
#Mann= 3 , 0 , 0
       0     0.1       0   452.6   0.045       0   467.6     0.1       0
Bank Sta=   452.6,   467.6
Exp/Cntr=0.3,0.1

Type RM Length L Ch R = 1 ,1858.6,332.487,329.742,326.997
XS GIS Cut Line= 3
     1768726.524      257028.856     1768348.098      257281.480
     1767969.673      257534.105
#Sta/Elev= 30
       0 1146.88    13.2 1144.87    27.5 1142.36    49.5 1137.30    83.1 1128.45
   177.2 1101.70   245.7 1084.95   298.7 1072.59   384.4 1053.81   398.7 1051.83
   447.7 1047.34   455.0 1047.03   462.7 1047.19   468.3 1047.35   508.4 1049.79
   529.8 1050.66   551.2 1051.13   584.2 1051.38   679.5 1050.91   712.7 1051.19
   727.0 1051.86   733.7 1053.00   741.3 1054.74   802.1 1072.50   844.9 1084.03
   855.5 1086.48   870.6 1089.42   884.0 1093.19   898.3 1098.62   910.0 1104.02
#Mann= 3 , 0 , 0
       0     0.1       0   447.7   0.045       0   462.7     0.1       0
Bank Sta=   447.7,   462.7
Exp/Cntr=0.3,0.1

Type RM Length L Ch R = 1 ,1528.8,395.178,400,404.822
XS GIS Cut Line= 3
     1768510.677      256715.311     1768164.837      257010.980
     1767818.998      257306.649
#Sta/Elev= 30
       0 1167.75    58.5 1149.77   167.8 1117.57   209.9 1104.34   240.9 1095.11
   259.2 1090.71   314.0 1078.50   369.9 1065.60   378.4 1063.16   386.6 1060.39
   412.0 1051.30   433.4 1045.08   441.9 1042.79   447.5 1041.62   449.0 1041.31
   460.1 1040.87   462.5 1040.93   496.7 1044.54   527.1 1046.56   574.0 1048.39
   647.8 1050.42   681.5 1051.67   699.0 1052.54   714.6 1054.45   761.4 1063.62
   777.1 1067.10   824.7 1080.12   839.5 1085.06   849.9 1089.15   910.0 1115.02
#Mann= 3 , 0 , 0
       0     0.1       0   447.5   0.045       0   462.5     0.1       0
Bank Sta=   447.5,   462.5
Exp/Cntr=0.3,0.1

Type RM Length L Ch R = 1 ,1128.8,535.548,519.275,502.69
XS GIS Cut Line= 3
     1768353.048      256458.152     1767952.326      256673.668
     1767551.605      256889.184
#Sta/Elev= 30
       0 1162.73     6.3 1160.47    19.8 1156.73    46.2 1150.82   121.4 1131.87
   235.5 1101.02   296.9 1085.57   316.4 1081.21   329.9 1077.68   368.3 1065.97
   410.8 1052.11   423.5 1048.53   437.7 1043.68   447.5 1041.00   451.2 1040.21
   462.5 1039.98   464.7 1039.92   547.5 1042.12   626.5 1045.40   642.7 1046.95
   666.9 1050.58   680.4 1054.02   720.8 1067.61   734.3 1071.72   747.8 1074.75
   800.5 1084.67   826.8 1090.88   842.2 1096.16   882.6 1111.19   910.0 1121.93
#Mann= 3 , 0 , 0
       0     0.1       0   447.5   0.045       0   462.5     0.1       0
Bank Sta=   447.5,   462.5
Exp/Cntr=0.3,0.1

Type RM Length L Ch R = 1 ,609.5,309.137,321.895,322.126
XS GIS Cut Line= 3
     1767825.405      255805.529     1767632.031      256312.984
     1767483.738      256769.124
#Sta/Elev= 30
       0 1042.45   139.3 1041.94   320.5 1040.18   353.4 1039.58   391.5 1041.13
   404.2 1041.16   467.7 1039.99     519 1037.76   531.3 1037.67     534 1037.77
   568.9 1039.34   681.3 1045.45   718.7 1047.93   731.2 1048.47   776.8 1049.30
   793.6 1050.06   806.1 1051.60   818.6 1054.80   856.0 1066.44   868.5 1070.00
   918.5 1083.20   927.6 1087.48   931.0 1089.61   943.4 1099.42   955.5 1107.92
   968.4 1115.91   974.6 1119.33   980.9 1122.04   993.5 1126.52  1022.7 1132.52
#Mann= 3 , 0 , 0
       0     0.1       0     519   0.045       0     534     0.1       0
Bank Sta=     519,     534
Exp/Cntr=0.3,0.1

Type RM Length L Ch R = 1 ,287.6,281.831,287.644,297.435
XS GIS Cut Line= 3
     1767674.660      255746.486     1767376.176      256219.271
     1767194.437      256653.399
#Sta/Elev= 30
       0 1042.16    67.2 1042.29   140.8 1039.74   229.8 1041.66   267.8 1041.78
   277.8 1041.13   296.5 1038.86   305.9 1038.55   363.2 1041.64   404.2 1042.27
   460.3 1042.16   518.9 1040.10   534.6 1039.01   562.6 1036.14   571.5 1035.79
   577.6 1035.99   635.9 1038.88   674.5 1040.04   700.2 1039.96   714.8 1039.35
   751.1 1036.02   777.5 1036.18   805.5 1038.50   829.0 1041.52   854.7 1046.68
   919.0 1058.47   931.9 1060.46   957.7 1062.20   970.5 1064.08  1029.8 1076.76
#Mann= 3 , 0 , 0
       0     0.1       0   562.6   0.045       0   577.6     0.1       0
#XS Ineff= 2 , 0
                             676         1040.09
Permanent Ineff=
       F       F
Bank Sta=   562.6,   577.6
Exp/Cntr=0.3,0.1